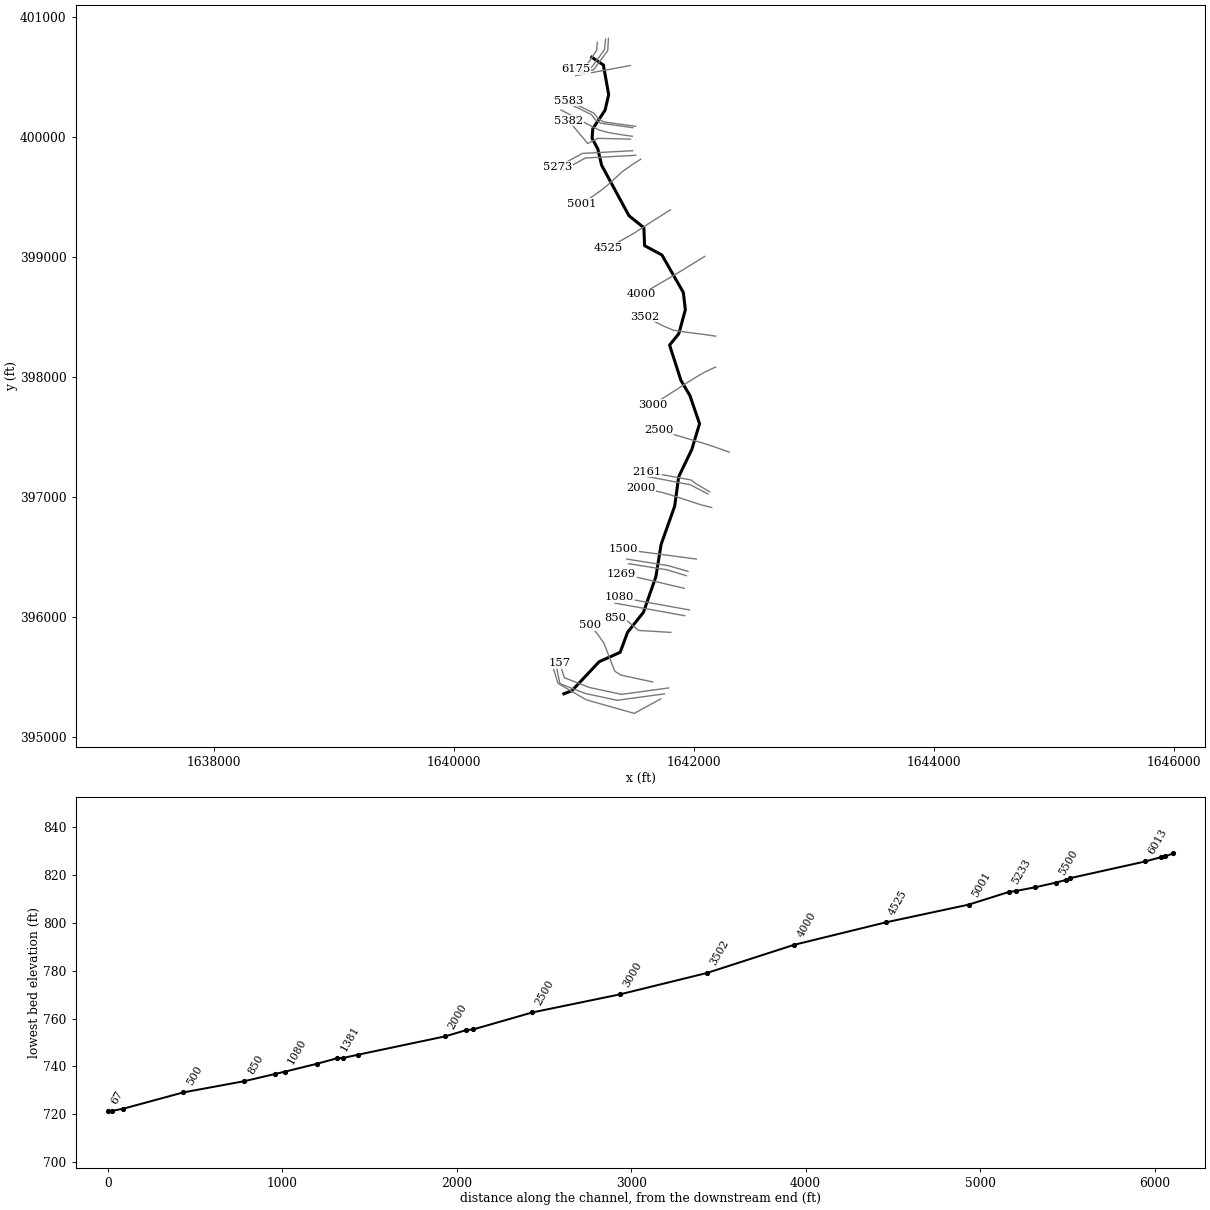
--- BARKERRN.prj (project) ---

Proj Title=BARKERRN
Current Plan=p01
Default Exp/Contr=0,0
English Units
Geom File=g01
Flow File=f01
Plan File=p01
BEGIN DESCRIPTION:
---------- MODELED AS PART OF WVEMD CTP PROGRAM, 2023----------
Stream Name: Barker Run
Flood Zone:  AFH
Wetzel County, WV
HEC-RAS Version: RAS 6.3
Vertical Datum: NAVD88
Projection: NAD 1983 StatePlane West Virginia S FIPS 4702 (US Feet)
Terrain: 1-meter West Virginia FEMA R3 South Central (collected 2018-2020)
Land Use: 2019 NLCD
Hydrologic Method:
WV 2010 Regional Regression Equations
Additional Model Notes:
None
END DESCRIPTION:
DSS File=dss
DSS Export Rating Curves= 0
DSS Export Rating Curve Sorted= 0
DSS Export Volume Flow Curves= 0
DXF OffsetX= 0
DXF OffsetY= 0
DXF ScaleX= 0
DXF ScaleY= 0

--- BARKERRN.p01 (plan) ---

Plan Title=Floodplain
Program Version=6.30
Short Identifier=Floodplain
Geom File=g01
Flow File=f01
Subcritical Flow
K Sum by GR= 0
Std Step Tol= 0.01
Critical Tol= 0.01
Num of Std Step Trials= 20
Max Error Tol= 0.3
Flow Tol Ratio= 0.001
Split Flow NTrial= 30
Split Flow Tol= 0.02
Split Flow Ratio= 0.02
Log Output Level= 0
Friction Slope Method= 1
Unsteady Friction Slope Method= 2
Unsteady Bridges Friction Slope Method= 1
Parabolic Critical Depth
Global Vel Dist= 0 , 0 , 0
Global Log Level= 0
CheckData=True
Encroach Param=-1 ,0,0, 0
Computation Interval=0.1SEC
Output Interval=1SEC
Instantaneous Interval=Max Profile
Mapping Interval=1HOUR
Computation Time Step Use Courant=        0
Computation Time Step Use Time Series=    0
Computation Time Step Count To Double=0
Computation Time Step Max Doubling=0
Computation Time Step Max Halving=0
Computation Time Step Residence Courant=0
Run HTab= 0
Run UNet= 0
Run Sediment= 0
Run PostProcess= 0
Run WQNet= 0
Run RASMapper=-1
UNET Theta= 0
UNET Theta Warmup= 0
UNET ZTol= 0
UNET ZSATol= 0
UNET MxIter= 0
UNET Max Iter WO Improvement= 0
UNET MaxInSteps= 0
UNET DtIC= 0
UNET DtMin= 0
UNET MaxCRTS= 0
UNET WFStab= 0
UNET SFStab= 0
UNET WFX= 1
UNET SFX= 1
UNET Gravity=32.17405
UNET 1D Methodology=Finite Difference
UNET DSS MLevel= 1
UNET Pardiso=0
UNET DZMax Abort= 0
UNET Use Existing IB Tables= 0
UNET Froude Reduction=False
UNET Froude Limit= 0
UNET Froude Power= 0
UNET D1 Cores= 0
UNET WindReference=Eulerian
UNET WindDragFormulation=Hsu (1988)
UNET D2 Coriolis=0
UNET D2 Cores= 0
UNET D2 Theta= 1
UNET D2 Theta Warmup= 1
UNET D2 Z Tol= 0.01
UNET D2 Volume Tol= 0.01
UNET D2 Max Iterations= 20
UNET D2 Equation= 0
UNET D2 RampUpFraction=0.1
UNET D2 TimeSlices= 1
UNET D2 Turbulence Formulation=Non-Conservative (original)
UNET D2 Eddy Viscosity=0.3
UNET D2 Transverse Eddy Viscosity=0.1
UNET D2 Smagorinsky Mixing=0
UNET D2 BCVolumeCheck=0
UNET D2 Cores=0
UNET D2 SolverType=PARDISO (Direct)
UNET D2 Minimum Iterations= 3
UNET D2 Maximum Iterations= 30
UNET D2 Restart Number= 10
UNET D2 Relaxation Coeff=1.3
UNET D2 SOR Precondition Iterations= 10
UNET D2 ILUT Maximum Fill= 8
UNET D2 ILUT Tolerance=1E-08
UNET D2 Convergence Tolerance=0.00001
UNET D1D2 MaxIter= 0
UNET D1D2 ZTol=0.01
UNET D1D2 QTol=0.1
UNET D1D2 MinQTol=1
DSS File=dss
Write IC File= 0
Write IC File at Fixed DateTime=0
Write IC File at Sim End=0
Echo Input=False
Echo Parameters=False
Echo Output=False
Write Detailed= 0
HDF Write Warmup=0
HDF Write Time Slices=0
HDF Flush=0
HDF Compression= 1
HDF Chunk Size= 1
HDF Spatial Parts= 1
HDF Use Max Rows=0
HDF Fixed Rows= 1
Calibration Method= 0
Calibration Iterations= 20
Calibration Max Change=0.05
Calibration Tolerance=0.2
Calibration Maximum=1.5
Calibration Minimum=0.5
Calibration Optimization Method= 1
WQ AD Non Conservative
WQ ULTIMATE=-1
WQ Max Comp Step=1HOUR
WQ Output Interval=15MIN
WQ Output Selected Increments= 0
WQ Output face flow=0
WQ Output face velocity=0
WQ Output face area=0
WQ Output face dispersion=0
WQ Output cell volume=0
WQ Output cell surface area=0
WQ Output cell continuity=0
WQ Output cumulative cell continuity=0
WQ Output face conc=0
WQ Output face dconc_dx=0
WQ Output face courant=0
WQ Output face peclet=0
WQ Output face adv mass=0
WQ Output face disp mass=0
WQ Output cell mass=0
WQ Output cell source sink temp=0
WQ Output nsm pathways=0
WQ Output nsm derived pathways=0
WQ Create Restart=0
WQ Fixed Restart=0
WQ System Summary=0
WQ Write To DSS=0
Sorting and Armoring Iterations= 10
XS Update Threshold= 0.02
Bed Roughness Predictor= 0
Hydraulics Update Threshold= 0.02
Energy Slope Method= 1
Volume Change Method= 1
Sediment Retention Method= 0
Sediment TS Multiplier= 1
Warm Up Method= 0
XS Weighting Method= 0
Number of US Weighted Cross Sections= 1
Number of DS Weighted Cross Sections= 1
Upstream XS Weight=0
Main XS Weight=1
Downstream XS Weight=0
Number of DS XS's Weighted with US Boundary= 1
Upstream Boundary Weight= 1
Weight of XSs Associated with US Boundary= 0
Number of US XS's Weighted with DS Boundary= 1
Downstream Boundary Weight= 0.5
Weight of XSs Associated with DS Boundary= 0.5
Percentile Method= 0
Sediment Output Level= 3
Mass or Volume Output= 0
Output Increment Type= 1
Profile and TS Output Increment= 1
Transport Output Increment 1
XS Output Flag= 0
XS Output Increment= 10
Read HDF5 Sediment Hotstart= 0
Sediment Hotstart Type= 0
Write Gradation File= 0
Read Gradation Hotstart= 0
Write HDF5 File= 1
Write Binary Output= 1
Write DSS Sediment File= 0
DSS Sediment Output Type= 1
SV Curve= 0
Specific Gage Flag= 0
Subcell Erosion Methods= 0
Subcell Deposition Methods= 0
Advection Scheme= 1
Matrix Solver= 0
Implicit Weighting Factor= 1
Maximum Outer Loop Convergence Iterations= 5
Convergence Maximum Absolute= 0.001
Convergence RMSE= 0.0001
Grain Fractions Max Abs Error= 0.001
Max Subgrid Regions= 1
Max Subgrid Length Scale= 3.402823E+38
Initial Layer Thickness= 3.402823E+38
Min Layer Thickness= 3.402823E+38
Max Layer Thickness= 3.402823E+38
Number of Layers= 5

--- BARKERRN.f01 (steady flow) ---

Flow Title=Flow
Program Version=6.31
Number of Profiles= 1
Profile Names=F01pct
River Rch & RM=BARKERRN,Main,6175
     913
Boundary for River Rch & Prof#=BARKERRN,Main            , 1
Up Type= 0
Dn Type= 3
Dn Slope=0.01054
DSS Import GetInterval= 0
DSS Import GetPeak= 0
DSS Import FillOption= 0

--- BARKERRN.g01 (geometry) ---

Geom Title=Geometry
Program Version=6.30

River Reach=BARKERRN        ,Main
Reach XY= 30
1641148.29035705400664.9981159111641245.36335842400600.101748141
1641289.43815231400354.005772174     1641259.387      400223.461
     1641157.087      400069.224     1641151.185      399989.351
     1641199.188      399900.429     1641230.271      399765.472
     1641458.872      399343.681     1641582.813      399244.529
     1641588.714       399094.62     1641733.115      399017.108
     1641911.746      398703.913     1641928.271      398560.693
     1641873.974      398361.208     1641796.855      398266.384
     1641891.963      397971.193     1641966.248      397846.041
     1642046.704       397611.27     1641982.176      397396.834
     1641872.825      397169.413     1641839.334      396923.893
     1641726.269      396605.347     1641682.704      396336.156
     1641578.957       396039.77     1641447.005      395873.572
     1641385.059      395706.618     1641209.292      395627.548
     1640983.749      395386.9231640916.18068093395361.053688804

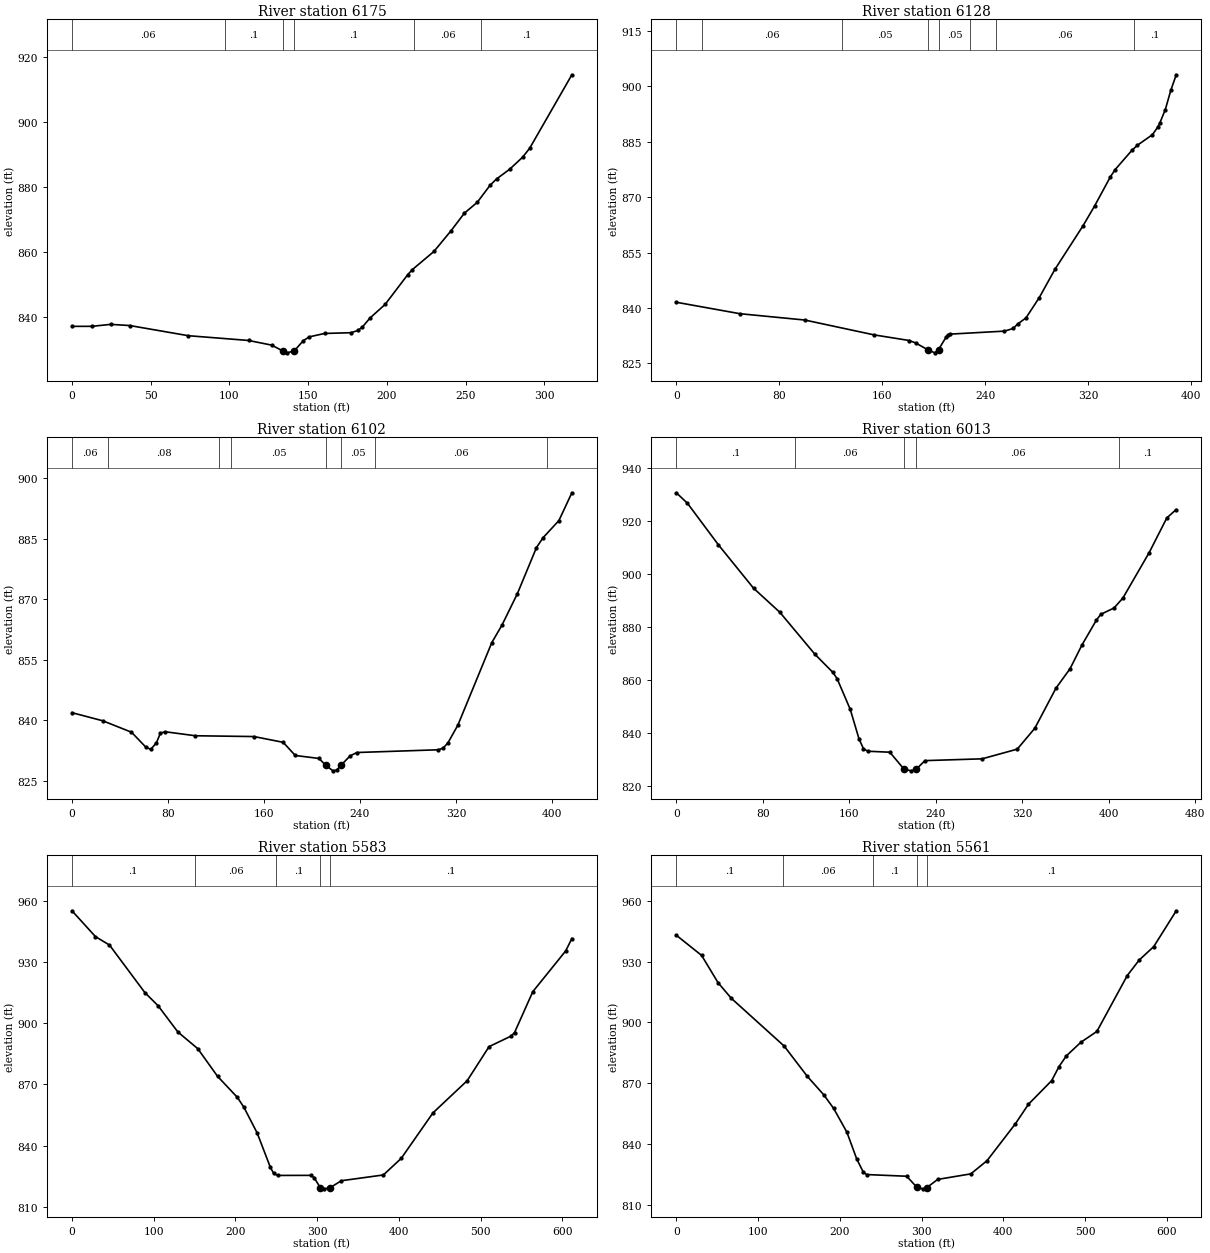
Type RM Length L Ch R = 1 ,6175    ,47.1,46.9,46.7
XS GIS Cut Line= 4
1641194.71933083400789.0768730931641189.11514302400722.336090996
1641098.93866645400586.8166403251641013.58838711400566.746595655
#Sta/Elev= 30
       0  837.16    12.6  837.17    24.6  837.77    36.7  837.41    73.9  834.29
   112.1  832.83   126.8   831.4   133.8  829.62   136.4  829.03   141.1   829.6
   146.9  832.79   150.8  833.95   160.4  834.98   177.1  835.21   181.5  835.89
   184.3   836.9   189.3  839.76   198.8  843.88   213.2  853.04   216.1  854.58
   229.8  860.15   240.7  866.52   249.1  871.89   257.3  875.23   265.5   880.5
   269.6  882.43   277.9   885.4   286.1  889.09   290.6  891.84   317.4  914.41
#Mann= 6 ,-1,0
       0     .06       0   96.98      .1       0   133.8    .045       0
   141.1      .1       0  216.98     .06       0  259.76      .1       0
Bank Sta=133.8,141.1
XS Rating Curve= 0 ,0
Exp/Cntr(USF)=0,0
Exp/Cntr=0.3,0.1

Type RM Length L Ch R = 1 ,6128    ,27.1,26.5,26.2
XS GIS Cut Line= 5
1641263.62250465400815.1897949651641254.91053996400727.153099191
1641146.24024362400579.5082239861641112.76795824400573.088881585
 1641036.1943739400541.450694041
#Sta/Elev= 30
       0  841.53    49.5  838.43    99.9  836.72   153.9  832.69   181.1  831.18
   186.1  830.51   195.3  828.71     201  827.84   203.9  828.74   209.6  832.02
   210.9  832.62   212.5   832.9   255.1  833.72   261.9  834.43   265.5  835.68
   271.8  837.27   282.1  842.74   294.3   850.4     316  862.12   325.2  867.58
   337.4  875.43   341.2  877.45   354.2  882.64   358.5  884.04   370.2  886.89
   374.2  888.89   375.8  889.94   380.2  893.69   384.5  898.94   388.7  903.11
#Mann= 8 ,-1,0
       0      .1       0      20     .06       0  128.47     .05       0
   195.3    .045       0   203.9     .05       0  228.47      .1       0
  248.47     .06       0  355.87      .1       0
Bank Sta=195.3,203.9
XS Rating Curve= 0 ,0
Exp/Cntr(USF)=0,0
Exp/Cntr=0.3,0.1

Type RM Length L Ch R = 1 ,6102    ,92.8,89,83.8
XS GIS Cut Line= 5
1641287.46577642400822.0676618221641281.50495848400719.358183419
1641163.20564853400558.874623413 1641119.6458251400553.830854385
1641053.61830327400529.070533698
#Sta/Elev= 30
       0  841.85    25.6  839.84    49.6     837    61.4  833.34    65.6  832.72
    70.4  834.38    73.7  836.78    77.7  837.11   102.9  836.12   151.7  835.92
     176  834.49   186.1  831.22   205.8  830.49   211.7  828.75   217.5  827.41
   220.7   827.6  224.11  828.77   231.8  831.13   237.5  831.96   305.4  832.64
   309.4  833.07   313.4  834.39   321.6  838.75   349.9  859.26   358.4  863.61
   371.2   871.4   387.1  882.84   392.6  885.29   405.8  889.54   416.6  896.44
#Mann= 8 ,-1,0
       0     .06       0      30     .08       0  122.88     .06       0
  132.88     .05       0   211.7    .045       0  224.11     .05       0
  252.88     .06       0  396.11      .1       0
Bank Sta=211.7,224.11
XS Rating Curve= 0 ,0
Exp/Cntr(USF)=0,0
Exp/Cntr=0.3,0.1

Type RM Length L Ch R = 1 ,6013    ,432,429.6,423.5
XS GIS Cut Line= 2
1641470.28232095400595.6564819651641015.47425756400511.432766522
#Sta/Elev= 30
       0  930.74    10.3  926.76    38.8  911.13    71.4  894.68    95.8  885.55
   128.3  869.66   144.6  862.95   148.7  860.53   160.9  848.87     169  837.72
   173.1  834.03   177.1  833.06   197.5  832.69   210.5  826.35   217.3  825.65
  222.11826.3345     230  829.51   282.9  830.19   315.4  833.85   331.7  841.77
   351.2  856.88   364.3  864.28   375.2  873.16   388.7  882.67   392.7  884.81
   404.9  887.19   413.1  890.93   437.5  908.16   453.8  921.25   462.5  924.42
#Mann= 5 ,-1,0
       0      .1       0     110     .06       0   210.5    .045       0
  222.11     .06       0     410      .1       0
Bank Sta=210.5,222.11
XS Rating Curve= 0 ,0
Exp/Cntr(USF)=0,0
Exp/Cntr=0.3,0.1

Type RM Length L Ch R = 1 ,5583    ,21.2,21.5,21.2
XS GIS Cut Line= 5
1641512.50015309400089.1017120491641247.19544944  400126.0548672
1641200.76712631400153.5328543631641168.55155515400197.118627105
1640957.25530903400301.345474967
#Sta/Elev= 30
       0  955.36    28.7  942.68    45.9  938.51    89.2  915.15   105.4  908.68
   129.6  895.77   153.9   887.6   178.1     874   202.3  863.68   210.4  858.75
   226.6  846.14   242.7  829.29   246.7  826.36   251.5  825.29   292.3  825.32
   296.3  824.22   303.9   819.2   308.6   818.7   315.7  819.25   329.6  822.69
     381  825.52   402.8  833.67   441.6  856.01   483.5  871.84   510.3   888.6
   537.1  893.75   541.5  895.52   563.8   915.6     604  935.61   611.6  941.71
#Mann= 5 ,-1,0
       0      .1       0     150     .06       0     250      .1       0
   303.9    .045       0   315.7      .1       0
Bank Sta=303.9,315.7
XS Rating Curve= 0 ,0
Exp/Cntr(USF)=0,0
Exp/Cntr=0.3,0.1

Type RM Length L Ch R = 1 ,5561    ,61,61,61.3
XS GIS Cut Line= 5
1641490.70726672400077.7315104641641225.40256307400114.684665615
1641178.97423993400142.1626527791641146.75866878400185.748425521
1640935.46242266400289.975273382
#Sta/Elev= 30
       0  942.98    30.9  933.04    51.1  919.56    67.2  911.92   131.9  888.37
   160.1   873.5   180.3  864.36   192.4  857.66   208.6  845.96   220.7   832.7
   228.8  826.18   232.8  825.04   281.8  824.21   294.5818.6825   301.9     818
   306.5  818.65   319.8  822.65   360.3  825.38   380.1  831.88   414.6  849.95
   430.8   859.7   459.2  871.33   468.2  878.27   477.1  883.51   494.9  890.23
   514.5  895.57   551.7  923.13   566.3  930.77   584.1   937.4   611.6  955.04
#Mann= 5 ,-1,0
       0      .1       0     130     .06       0     240      .1       0
   294.5    .045       0   306.5      .1       0
Bank Sta=294.5,306.5
XS Rating Curve= 0 ,0
Exp/Cntr(USF)=0,0
Exp/Cntr=0.3,0.1

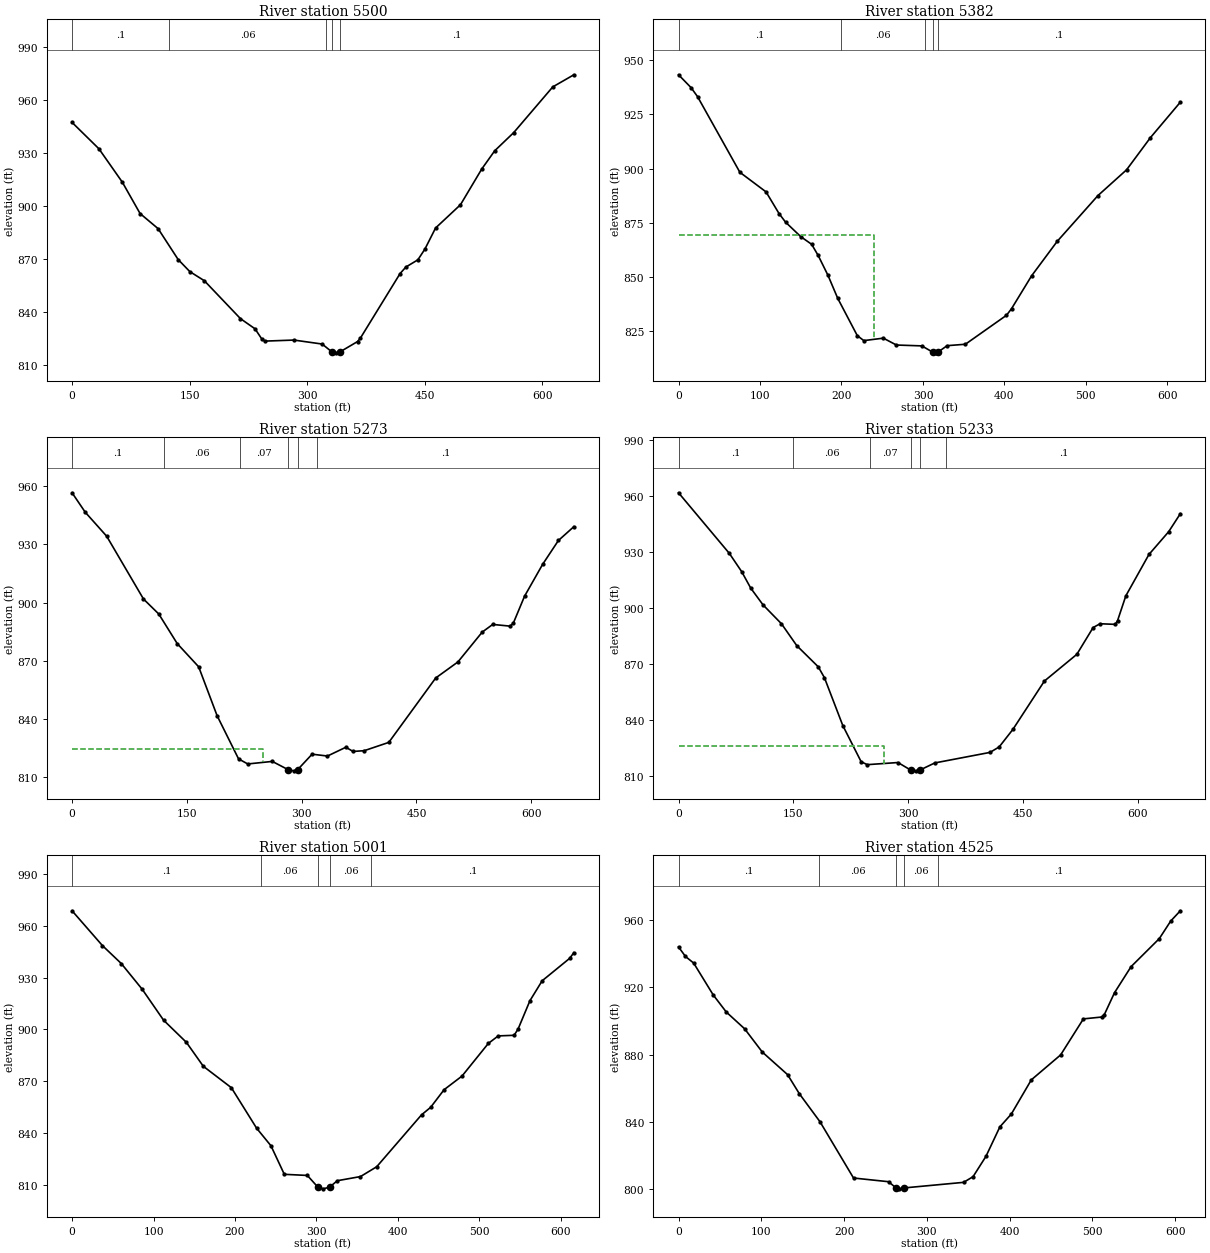
Type RM Length L Ch R = 1 ,5500    ,115.5,118.3,123.1
XS GIS Cut Line= 6
1641486.04629217400005.8945120131641383.52320325400020.746516421
1641286.60082492400037.1372316781641207.16167934400058.634235919
1641118.47320843400104.8431330031640892.37129842 400225.43344301
#Sta/Elev= 30
       0   947.1    34.3  932.18    64.1  913.34    86.8  895.58   109.8  887.04
   135.4  869.57   150.3  862.74   168.8  857.59   214.9  836.15   233.5  830.39
   241.8  824.86   245.9  823.44   283.2  824.03   319.2  821.78   331.6  817.33
   337.2  816.81   341.8817.3165   364.3  823.18   367.9  825.08   418.6  861.63
     426  865.32   441.3   869.4   450.3  875.46   463.9  887.39   495.7  900.56
   522.9  920.79   539.4  931.07   563.7  941.37   613.5  967.19   640.4  974.04
#Mann= 5 ,-1,0
       0      .1       0  123.59     .06       0  324.19      .1       0
   331.6    .045       0   341.8      .1       0
Bank Sta=331.6,341.8
XS Rating Curve= 0 ,0
Exp/Cntr(USF)=0,0
Exp/Cntr=0.3,0.1

Type RM Length L Ch R = 1 ,5382    ,111,109.3,106.1
XS GIS Cut Line= 4
1641471.44109181399982.3481527241641199.39849093399988.875490671
1641114.75365691399945.7108365061640955.36027543400136.688111275
#Sta/Elev= 30
       0  943.29    15.3  937.39    23.3  933.22    75.3  898.25   107.4  889.21
   123.4  879.17   131.4  875.21     150  868.54   163.4  864.99   171.4  859.83
   183.4  850.69   195.4  840.04   219.4  822.82   227.4  820.52   251.4  821.65
   267.4  818.48   298.6  818.08   312.3815.1266   316.2  814.87   318.1815.1194
   329.7  818.18   352.1  818.84   402.5  832.21   408.7  835.24   433.3  850.41
   464.7  866.32   514.8  887.51   549.9  899.39   579.2  914.26   615.9  930.63
#Mann= 5 ,-1,0
       0      .1       0     200     .06       0  302.12      .1       0
   312.3    .045       0   318.1      .1       0
#XS Ineff= 2 , 0
          240.04  869.35
Permanent Ineff=
       F       F
Bank Sta=312.3,318.1
XS Rating Curve= 0 ,0
Exp/Cntr(USF)=0,0
Exp/Cntr=0.3,0.1

Type RM Length L Ch R = 1 ,5273    ,39.8,39.9,39.8
XS GIS Cut Line= 3
1641489.28599152399885.8593587191641070.48356648399863.118955549
1640862.97738755399750.364456499
#Sta/Elev= 30
       0  956.48    17.2  946.48    45.2  934.13    93.3   901.8   113.3  894.08
   137.4  878.85   165.4  866.91   189.5  841.73   217.5  819.53   229.5   816.9
   261.6  818.21   282.1814.0088   289.6  813.36   294.8 813.988   313.6  821.93
   333.7  820.98   357.7   825.5   367.1  823.34   381.7  823.73   413.8     828
   475.1  861.15   504.1   869.4   535.9  884.78   549.6  888.72   572.3  887.84
   576.5  889.37   591.2  903.26   614.8  919.64   635.4  931.92   655.6  939.03
#Mann= 6 ,-1,0
       0      .1       0     120     .06       0     220     .07       0
   282.1    .045       0   294.8     .07       0     320      .1       0
#XS Ineff= 2 , 0
           249.1  824.85
Permanent Ineff=
       F       F
Bank Sta=282.1,294.8
XS Rating Curve= 0 ,0
Exp/Cntr(USF)=0,0
Exp/Cntr=0.3,0.1

Type RM Length L Ch R = 1 ,5233    ,227.2,232.2,235.8
XS GIS Cut Line= 3
1641514.39518669 399847.484928371641095.59276165  399824.7445252
1640888.08658272 399711.99002615
#Sta/Elev= 30
       0  961.87    66.4   929.4    82.4   919.7    94.4  910.77   110.4  901.84
   134.5  891.72   154.5     880   182.5  868.69   190.6  862.86   214.6  837.23
   238.6  817.83   246.6  816.27   286.7  817.41   303.5 813.325   310.7  812.96
   315.2  813.34   334.8  817.19   406.9  822.83   418.9  825.75   436.9  835.18
     478  861.04   520.4  875.36   541.7  889.72   550.8  891.73   570.7   891.4
   573.6  893.42   584.4  906.67   614.6  928.83   640.4  941.04   655.6  950.66
#Mann= 6 ,-1,0
       0      .1       0     150     .06       0     250     .07       0
   303.5    .045       0   315.2     .07       0     350      .1       0
#XS Ineff= 2 , 0
          268.22  826.36
Permanent Ineff=
       F       F
Bank Sta=303.5,315.2
XS Rating Curve= 0 ,0
Exp/Cntr(USF)=0,0
Exp/Cntr=0.3,0.1

Type RM Length L Ch R = 1 ,5001    ,476.6,475.9,474
XS GIS Cut Line= 6
1641556.80435276399815.4201554211641477.61520667399764.111531004
1641405.87584884399713.3134042621641276.32459876399595.590214506
1641216.80437659399548.6785629241641067.81911026399442.794260249
#Sta/Elev= 30
       0  968.67    37.3  948.49    60.4  938.12    86.2  923.14   112.3  905.31
   140.3  892.48   161.1   878.6   195.5  866.21   226.5  842.75   244.1  832.58
   260.5  816.03   288.8  815.38   301.6  808.66   308.3  807.62   316.1808.6314
   325.6  812.33     354  814.73   373.9  820.41   428.9  850.47   440.1  854.82
   456.6  865.03   478.6  872.93     511  891.88   523.1   896.2   542.6  896.55
   547.5  900.23     562   916.6     577  928.13   610.7   941.1   615.9  944.41
#Mann= 5 ,-1,0
       0      .1       0  232.26     .06       0   301.6    .045       0
   316.1     .06       0  367.31      .1       0
Bank Sta=301.6,316.1
XS Rating Curve= 0 ,0
Exp/Cntr(USF)=0,0
Exp/Cntr=0.3,0.1

Type RM Length L Ch R = 1 ,4525    ,524.8,524.9,523.9
XS GIS Cut Line= 4
1641803.61828749399392.6376749971641639.84655727399289.581886862
1641499.88379935399197.616825335 1641285.9936253  399077.6581479
#Sta/Elev= 30
       0  943.95     8.4   938.3    18.3  934.37    41.9  915.44    57.7  905.28
    79.8  895.34   101.2  881.49   131.7  868.09   145.9  856.76   170.9  840.07
   211.4  806.63   253.7  804.44  262.75  800.76   266.3   800.2     272  800.72
   344.3  804.05   355.8  807.42   371.4  819.52   388.2  837.03     402  844.63
   426.2  864.98   461.6   879.8   489.1  901.21   511.4  902.32   514.4  903.76
   526.7  916.77   546.7  932.26   580.8  948.91   594.6  959.36   606.2  965.46
#Mann= 5 ,-1,0
       0      .1       0     170     .06       0  262.75    .045       0
     272     .06       0   313.5      .1       0
Bank Sta=262.75,272
XS Rating Curve= 0 ,0
Exp/Cntr(USF)=0,0
Exp/Cntr=0.3,0.1

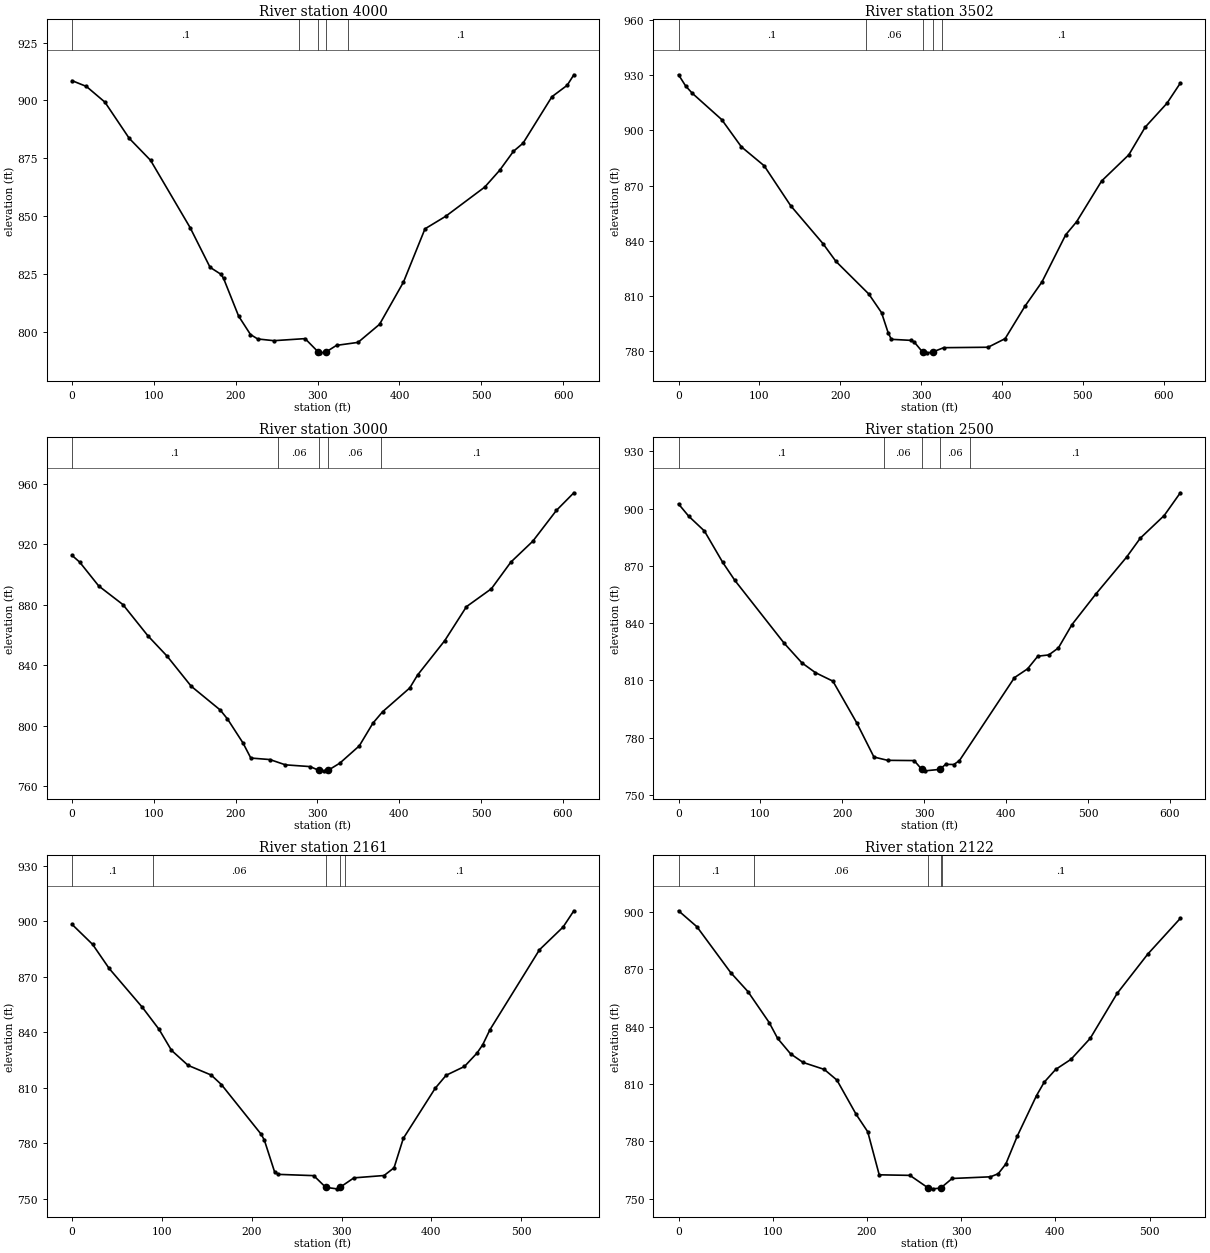
Type RM Length L Ch R = 1 ,4000    ,502.3,498.4,494.6
XS GIS Cut Line= 6
1642091.07756242399005.4700036791642010.77555767398956.356256753
 1641936.1356151398910.2087112521641872.08259359398871.175980926
1641721.24365643 398782.44814001  1641565.017919398690.551342174
#Sta/Elev= 30
       0  908.52    17.5  906.03    40.1  899.25    69.8   883.6    95.9  874.08
   144.3  844.93   168.6  827.81   181.9  824.79   185.1  823.02   203.5   806.7
     218  798.74   226.8  796.82   246.6  796.08   284.7  796.97   300.4791.3162
   303.3  790.82   310.8 791.304   323.1  794.05   349.4  795.34   375.7  803.16
   404.9  821.41   431.2  844.45   456.4  849.85   504.2   862.5   522.4  869.74
   539.3  877.97     551  881.48   586.3  901.58   604.9  906.51   613.1  911.07
#Mann= 5 ,-1,0
       0      .1       0  276.89     .06       0   300.4    .045       0
   310.8     .06       0  336.89      .1       0
Bank Sta=300.4,310.8
XS Rating Curve= 0 ,0
Exp/Cntr(USF)=0,0
Exp/Cntr=0.3,0.1

Type RM Length L Ch R = 1 ,3502    ,497.1,501.6,505.8
XS GIS Cut Line= 6
1642180.96517792398340.5937087541642088.18682018398354.203261584
 1641926.9994785398374.8229710011641828.15879692398390.322283834
1641757.24456868 398419.782854841641589.35710917398503.445089087
#Sta/Elev= 30
       0  930.22     8.9  924.07      17  920.18    53.4  905.87    77.7  891.07
   105.9  880.78   138.7  859.07   178.6  838.48   194.7  828.79   235.3  811.08
   251.1  800.93   259.2  790.12   263.2  786.43   287.5  785.86   291.6  784.92
   301.8779.5536   307.8  779.08   314.5779.5556     328  781.88   382.9  782.12
     404   786.8   428.4  804.35   449.5  817.58   478.9  843.23   492.3  850.27
   523.4  872.52     557  886.73   577.2  901.73   604.1   914.7   620.7  925.69
#Mann= 5 ,-1,0
       0      .1       0  231.27     .06       0   301.8    .045       0
   314.5     .06       0  326.27      .1       0
Bank Sta=301.8,314.5
XS Rating Curve= 0 ,0
Exp/Cntr(USF)=0,0
Exp/Cntr=0.3,0.1

Type RM Length L Ch R = 1 ,3000    ,506.4,500,491
XS GIS Cut Line= 6
1642180.51931268398083.4390393351642094.81377542398043.637281671
1642018.81983292398000.0487861781641955.20709926397960.309364334
1641871.03043035397906.3252203321641655.32646543397767.992819846
#Sta/Elev= 30
       0  912.69     9.3  908.26    32.6  892.46    62.2  880.13    92.8  859.42
   116.1  846.05   145.6  826.11   181.1  810.36     190  804.41   208.9  788.58
   218.5  778.56   241.9  777.55   260.8  774.06     291   772.9   301.3770.4854
   308.3  770.09   313.1  770.47   327.3  775.18   351.1  786.61   367.8  801.68
   379.6   809.2   412.8  824.96   422.3  833.48   455.6  856.31   482.1  878.77
   512.6  890.64   536.4  908.27   563.2  922.09   592.1  942.51   613.4  954.16
#Mann= 5 ,-1,0
       0      .1       0   252.1     .06       0   301.3    .045       0
   313.1     .06       0  377.11      .1       0
Bank Sta=301.3,313.1
XS Rating Curve= 0 ,0
Exp/Cntr(USF)=0,0
Exp/Cntr=0.3,0.1

Type RM Length L Ch R = 1 ,2500    ,337.3,338.6,338.2
XS GIS Cut Line= 6
1642293.94657926 397374.506402091642205.44019459397405.846890584
1642122.59554401 397434.282529251642050.99627776397456.641408429
1641955.03944868397484.7889899161641709.14722392397556.920079261
#Sta/Elev= 30
       0  902.45    12.4  896.04    31.6  888.28      54   871.8    68.8  862.37
   129.1   829.4   150.6  819.18   167.2  814.03   188.5  809.58   217.6  787.71
   238.6  769.81   255.3  768.09   287.7  767.96     297  763.36   301.2  762.58
   318.9763.3419   326.2     766   336.1   765.9   342.9  767.89   410.2  811.44
   426.2  816.04   438.7  822.67   452.1  823.33   463.8  826.99   480.4  839.23
   509.6  855.27   547.1  874.59   563.8  884.51     593  896.39   612.7  908.31
#Mann= 5 ,-1,0
       0      .1       0  251.48     .06       0     297    .045       0
   318.9     .06       0  356.49      .1       0
Bank Sta=297,318.9
XS Rating Curve= 0 ,0
Exp/Cntr(USF)=0,0
Exp/Cntr=0.3,0.1

Type RM Length L Ch R = 1 ,2161    ,39.5,39.5,39.5
XS GIS Cut Line= 4
1642131.93160307397043.8820254841642017.30251675397110.301821214
1641976.49228221 397142.392154631641608.23021623 397209.59754176
#Sta/Elev= 30
       0  898.33    22.9  887.52    41.3  874.53    78.4  853.45    96.9  841.61
   110.7   830.3   129.2  822.18   154.9  816.96   166.3   811.8   210.6  784.94
   214.1  781.79   225.4  764.78   229.5  763.31   269.1  762.62   282.4  756.31
   294.6  755.49   298.6   756.4   313.8  761.42   347.4  762.69   358.5  766.86
   368.8  782.74   404.3   809.8   416.5  816.84   436.9  821.59   450.8  828.79
   457.2  833.31   465.3  841.47   520.4  884.62   546.7   896.9   558.7  905.69
#Mann= 5 ,-1,0
       0      .1       0      90     .06       0   282.4    .045       0
   298.6     .06       0   304.4      .1       0
Bank Sta=282.4,298.6
XS Rating Curve= 0 ,0
Exp/Cntr(USF)=0,0
Exp/Cntr=0.3,0.1

Type RM Length L Ch R = 1 ,2122    ,122.6,121.9,120.8
XS GIS Cut Line= 4
 1642117.3611795397025.3153073561642012.84565903397079.846626769
1641967.16286736397103.245129818 1641610.1475377397171.251112405
#Sta/Elev= 30
       0  900.55    19.5  892.21    55.5  868.16    73.6  858.35    96.2  842.14
   105.2  833.83   118.9  825.78   132.2  821.27   154.7  817.62   168.1  812.05
   188.6  794.07   200.8  785.05     213  762.53   245.6  762.24   265.3  755.55
     270   755.2   278.2   755.6   290.4  760.61   331.1  761.49   339.3  763.09
   347.4   768.2   359.6  782.82     380  803.99   388.1  810.93   400.3  817.62
   416.6  822.92     437  833.89   465.5  857.33   498.1  877.94   532.6  896.59
#Mann= 5 ,-1,0
       0      .1       0      80     .06       0   265.3    .045       0
   278.2     .06       0  279.21      .1       0
Bank Sta=265.3,278.2
XS Rating Curve= 0 ,0
Exp/Cntr(USF)=0,0
Exp/Cntr=0.3,0.1

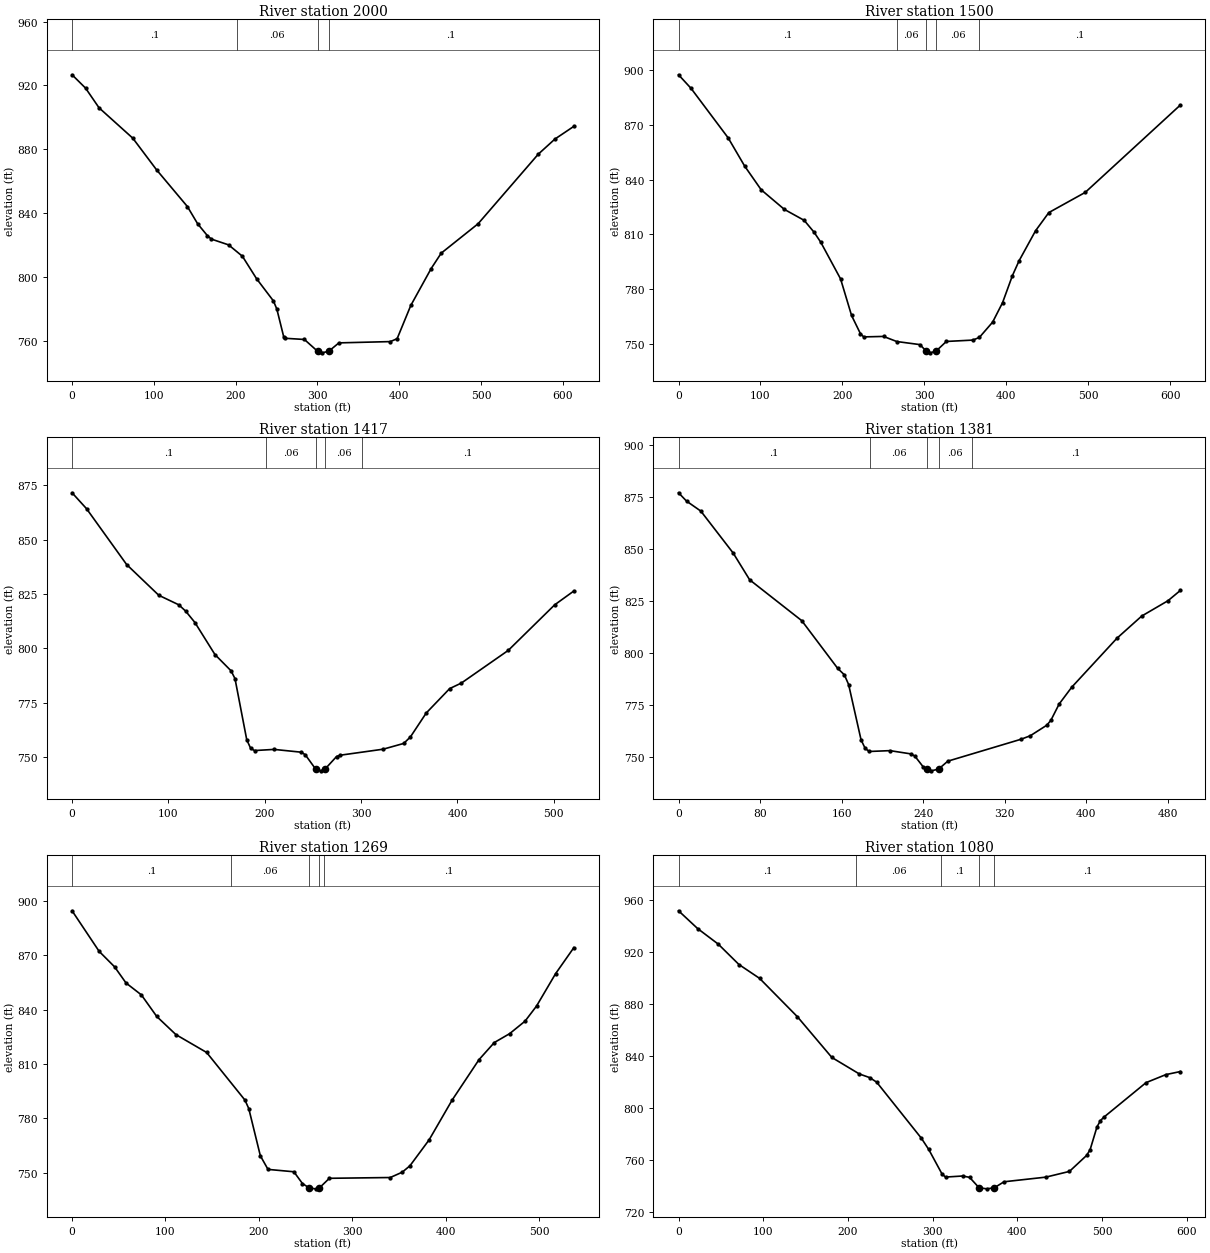
Type RM Length L Ch R = 1 ,2000    ,499.1,500,501.4
XS GIS Cut Line= 6
1642148.07482375 396912.697942511642057.09075376396935.902292416
1641807.55942868 397017.405410261641735.53266984397038.495919257
1641649.93933709397058.2130714211641557.37357734397076.322287172
#Sta/Elev= 30
       0  926.71    16.5  918.35      33  906.02    74.3  886.98   103.3  867.21
     141   844.2   153.6  833.36   165.4  826.01   170.4   823.8   191.4  820.19
   208.3  813.06   225.6  799.01   246.2   785.1   250.4  779.98   258.8  762.63
   260.4   761.7   284.1  760.95   300.3 753.525   305.2  752.58   313.7   753.5
   326.3  758.82   389.2  759.62   397.5  761.45   414.2  782.25   439.1  805.36
   451.4     815   496.5  833.41   570.1     877   590.4  886.44   613.6  894.42
#Mann= 4 ,-1,0
       0      .1       0  201.41     .06       0   300.3    .045       0
   313.7      .1       0
Bank Sta=300.3,313.7
XS Rating Curve= 0 ,0
Exp/Cntr(USF)=0,0
Exp/Cntr=0.3,0.1

Type RM Length L Ch R = 1 ,1500    ,83.2,83.2,82.9
XS GIS Cut Line= 6
1642020.15611634 396483.411071421641766.13661125396517.148208678
1641667.00721633396530.3138647531641592.66025217396540.188516915
1641505.92190859396551.7098193321641413.00608392396564.188468918
#Sta/Elev= 30
       0  897.58    15.3  890.11    60.6  862.92    80.7  847.45   100.9  834.42
   129.2  823.66   153.4  817.64   165.5   811.1   173.6  805.64   197.8  785.49
   211.2  765.41     222  755.45     226  753.65   250.2  753.91   266.4  751.11
   294.6  749.42     302746.0123   307.4   744.9   314.8  746.04   326.9  751.15
   359.2   751.9   367.2  753.36   383.4  761.76   395.5  772.43   407.6  787.36
   415.7  795.47   435.8  811.94     452  821.92   496.4  832.99   612.5  880.95
#Mann= 5 ,-1,0
       0      .1       0  266.25     .06       0     302    .045       0
   314.8     .06       0  366.25      .1       0
Bank Sta=302,314.8
XS Rating Curve= 0 ,0
Exp/Cntr(USF)=0,0
Exp/Cntr=0.3,0.1

Type RM Length L Ch R = 1 ,1417    ,35.7,35.7,35.7
XS GIS Cut Line= 3
1641950.47008942396380.6804740381641786.25183858396428.567992082
1641440.83528653396483.318690866
#Sta/Elev= 30
       0  871.63      15  864.31    56.6   838.6      90  824.43   110.8  820.03
   117.9  817.13   127.5  811.89   148.3  797.13     165  789.65   169.1  786.04
   181.3  757.88   185.4   753.9   189.4  752.92   209.7  753.45     238  752.16
   242.1  750.95   252.9744.3278   258.3  743.58   262.3  744.27   274.5  750.16
   278.5  750.79   322.9  753.55   344.2   756.2   351.2  759.22   367.6  770.22
   391.9  781.45   404.1  784.02   452.7  799.04   500.9  820.03   520.8   826.4
#Mann= 5 ,-1,0
       0      .1       0  201.06     .06       0   252.9    .045       0
   262.3     .06       0  301.06      .1       0
Bank Sta=252.9,262.3
XS Rating Curve= 0 ,0
Exp/Cntr(USF)=0,0
Exp/Cntr=0.3,0.1

Type RM Length L Ch R = 1 ,1381    ,112.8,112.5,112.1
XS GIS Cut Line= 3
1641935.64240164396344.7465258071641775.24725161396394.178657795
1641454.68260824396444.972261511
#Sta/Elev= 30
       0  876.96     7.9  872.94    21.9  868.15    53.6  848.03    69.8  835.16
   120.9  815.55   156.2  792.61   162.7  789.55   166.9  784.88   179.1  758.31
   183.2  754.15   187.2  752.72   207.5  753.12   227.7  751.58   231.8  750.55
   239.9  745.44   243.7 744.091     248  743.42   255.2744.2608   264.2  748.06
   336.3  758.62   345.2  760.28   361.4  765.34   365.4  767.71   373.5  775.52
   385.9  783.62   430.2   807.1   454.5  817.75   480.3  825.12   492.4  830.05
#Mann= 5 ,-1,0
       0      .1       0  187.84     .06       0   243.7    .045       0
   255.2     .06       0  287.84      .1       0
Bank Sta=243.7,255.2
XS Rating Curve= 0 ,0
Exp/Cntr(USF)=0,0
Exp/Cntr=0.3,0.1

Type RM Length L Ch R = 1 ,1269    ,187.3,188.5,189
XS GIS Cut Line= 2
1641920.39980172396239.5920715611641397.15996953396361.716458954
#Sta/Elev= 30
       0  894.49      29  872.12    45.5   863.6    57.8  854.67    74.2  848.12
    90.7  836.21   111.2  826.22   144.1  816.37   185.1  790.13   189.2  785.46
   201.6  759.42   209.8  751.91   237.5   750.6   246.7   744.1   254.1  741.64
   260.8  741.19   264.6741.5876   275.5     747   340.7  747.43   353.5  750.36
   361.8  753.91   382.3  768.18   406.9  790.08   435.7  812.39   452.1  821.84
   468.5  826.73     485  833.62   497.3  841.93   517.8  859.87   537.3  874.18
#Mann= 5 ,-1,0
       0      .1       0     170     .06       0   254.1    .045       0
   264.6     .06       0     270      .1       0
Bank Sta=254.1,264.6
XS Rating Curve= 0 ,0
Exp/Cntr(USF)=0,0
Exp/Cntr=0.3,0.1

Type RM Length L Ch R = 1 ,1080    ,54.7,54.4,54.5
XS GIS Cut Line= 2
1641962.26859396396059.5500265111641379.25374717396164.742307735
#Sta/Elev= 30
       0  951.76    22.5   938.1    46.9   926.1    71.3  910.42    95.7  899.75
   140.4  870.18     181  838.89   213.5  826.18   225.7  823.39   233.9  819.89
   286.7  776.73   295.4  768.08   311.1  749.19   315.2  746.86   335.5  747.68
   343.6  746.63   354.8738.6368   363.9   737.8   372.8738.6323   384.3  743.24
   433.6   746.8   461.5  751.22   481.8  763.53   485.9  767.93     494  785.45
   498.1  790.29   502.1  792.92   551.9  819.51   575.3  825.69   592.4  828.05
#Mann= 5 ,-1,0
       0      .1       0     210     .06       0     310      .1       0
   354.8    .045       0   372.8      .1       0
Bank Sta=354.8,372.8
XS Rating Curve= 0 ,0
Exp/Cntr(USF)=0,0
Exp/Cntr=0.3,0.1

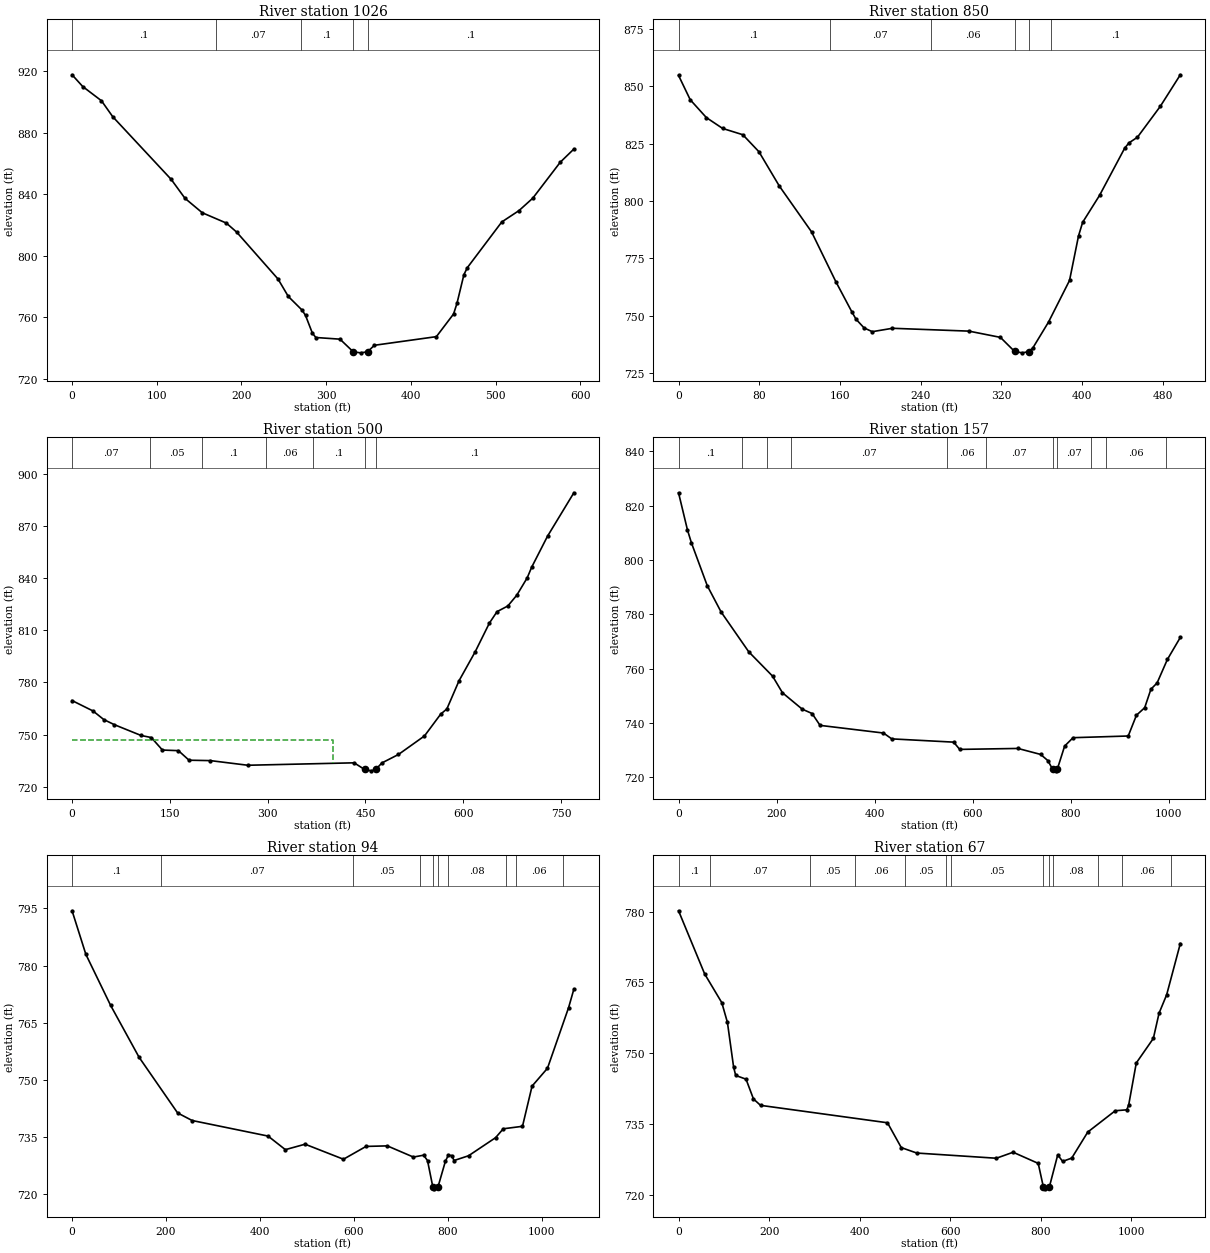
Type RM Length L Ch R = 1 ,1026    ,178.8,175.7,170
XS GIS Cut Line= 2
1641923.34150684396011.5102370641641340.32666005396116.702518287
#Sta/Elev= 30
       0  917.65    12.6     910    34.7  900.76      48   890.4   117.1  849.59
   133.3  837.33   153.7  827.95   182.1  821.24   194.3  815.37   243.1  784.89
   255.3  773.51   271.5  764.68   275.6  761.21   283.7  749.66   287.8  746.84
   316.3  745.76     332737.5271   340.6  736.87   348.8  737.54   356.9  741.78
   430.1   747.4   450.4  762.14   454.4  769.03   462.6  787.71   466.6  792.22
   507.3  821.96   527.6  829.33   543.9  837.42   576.4  860.83   592.4  869.35
#Mann= 5 ,-1,0
       0      .1       0     170     .07       0     270      .1       0
     332    .045       0   348.8      .1       0
Bank Sta=332,348.8
XS Rating Curve= 0 ,0
Exp/Cntr(USF)=0,0
Exp/Cntr=0.3,0.1

Type RM Length L Ch R = 1 ,850     ,353.7,350,344.3
XS GIS Cut Line= 4
1641807.71117978395872.4433669061641538.66319989395888.820200465
1641446.25106767395966.0252729551641343.31097102 395996.43939242
#Sta/Elev= 30
       0  854.76    11.6  844.14    27.6  836.37    43.7  831.65    63.7  828.91
    79.7  821.49    99.8  806.61   131.8   786.6   155.9  764.88   171.9  751.62
   175.9  748.52   183.9  744.73     192  743.09     212  744.57   287.8  743.33
     319  740.61   333.1734.4538   340.6  733.87   347.1 734.389   351.1  735.98
   366.7   747.3   387.5  765.41   396.4  784.82   400.5  790.75   417.2  802.44
   442.2  823.09   446.4  825.35   454.8  827.82   477.4  841.24   497.3  855.03
#Mann= 6 ,-1,0
       0      .1       0     150     .07       0     250     .06       0
   333.1    .045       0   347.1     .06       0  369.55      .1       0
Bank Sta=333.1,347.1
XS Rating Curve= 0 ,0
Exp/Cntr(USF)=0,0
Exp/Cntr=0.3,0.1

Type RM Length L Ch R = 1 ,500     ,339,343.4,349.6
XS GIS Cut Line= 6
1641655.65363702395460.0189711541641394.34068628395515.432580643
 1641340.6345095395548.5658282491641250.07596359395781.587671921
1641199.06130184395855.6370645021641133.43446459395930.410537004
#Sta/Elev= 30
       0  769.58    32.2  763.58    48.6  758.67      65  755.69   105.8  749.51
   121.5  748.32   138.6  741.12   163.1  740.78   179.4  735.28   212.2  735.05
   269.5  732.38   432.6  733.78   448.6  729.97   458.9  729.17   465.7 729.965
   475.2  733.71   500.6  738.58   540.5  749.24   565.5  761.84   574.8  764.74
   593.5  780.98   618.3  797.65   640.1  814.16   651.8  820.72   668.3  823.96
     682  830.13     698  840.11   704.9  846.27   729.2  864.09   769.6  889.06
#Mann= 7 ,-1,0
       0     .07       0     120     .05       0     200      .1       0
  297.12     .06       0  370.23      .1       0   448.6    .045       0
   465.7      .1       0
#XS Ineff= 2 , 0
          400.86  746.63
Permanent Ineff=
       F       F
Bank Sta=448.6,465.7
XS Rating Curve= 0 ,0
Exp/Cntr(USF)=0,0
Exp/Cntr=0.3,0.1

Type RM Length L Ch R = 1 ,157     ,63.2,63,63.8
XS GIS Cut Line= 5
1641790.14720991 395409.71068139 1641395.9237831395356.223080768
1641128.48577999395413.6727258811640920.47844424395494.894637936
1640880.85799934395617.718017143
#Sta/Elev= 30
       0   824.7    18.2  811.03    26.3  806.28    58.6  790.51    86.8  780.85
   143.3  766.17   191.8  757.24     212  751.11   252.3  745.08   272.5  743.47
   288.7  739.11   418.1  736.29     435  734.14   561.3  732.94   573.6  730.27
   692.4  730.62   738.7  728.42   753.4  726.16   763.1     723   769.6  722.38
   772.7  722.98   787.7   731.5   804.9  734.58   917.4   735.2   934.2  742.85
     951  745.61   963.7  752.42   976.3  754.72   997.3  763.37  1023.7  771.48
#Mann= 11 ,-1,0
       0      .1       0     130     .07       0     180      .1       0
     230     .07       0  547.84     .06       0  627.84     .07       0
   763.1    .045       0   772.7     .07       0  841.37     .08       0
  871.37     .06       0  994.68      .1       0
Bank Sta=763.1,772.7
XS Rating Curve= 0 ,0
Exp/Cntr(USF)=0,0
Exp/Cntr=0.3,0.1

Type RM Length L Ch R = 1 ,94      ,26.9,27,26
XS GIS Cut Line= 5
1641753.49829837395360.1851252591641359.27487157395306.697524636
1641091.83686846395364.147169749 1640883.8295327395445.369081805
1640847.36747713395615.568300948
#Sta/Elev= 30
       0  794.35    29.4  782.92    82.1  769.55   142.7  755.96   224.8  741.36
   255.7  739.38   417.4   735.3   454.3  731.74   496.3  733.17     578  729.23
   626.1  732.59   671.4  732.73   726.9   729.8   748.7  730.29     757  728.88
   768.2722.0587   771.4  721.47   779.5  722.05     795  728.65   801.2  730.27
   808.5   730.2   813.5  728.89   844.4  730.14     902  734.88   918.4  737.21
   959.3  737.86   979.7   748.4  1012.5  753.07  1057.5  768.97  1068.7   773.8
#Mann= 10 ,-1,0
       0      .1       0     190     .07       0  597.84     .05       0
  741.37     .07       0   768.2    .045       0   779.5     .07       0
  801.37     .08       0  924.68     .07       0  944.68     .06       0
 1044.68      .1       0
Bank Sta=768.2,779.5
XS Rating Curve= 0 ,0
Exp/Cntr(USF)=0,0
Exp/Cntr=0.3,0.1

Type RM Length L Ch R = 1 ,67      ,,,
XS GIS Cut Line= 5
1641722.79245357395318.5836581081641502.89898435395197.741301147
1641102.73249081395310.659569127 1640867.5773728395447.249749425
1640817.04314353395609.380401654
#Sta/Elev= 30
       0  780.18    57.8  766.79    95.6  760.72     108  756.54   121.7  747.06
   126.3  745.31   149.1  744.52   165.5  740.34   181.1  738.98   461.6  735.29
   492.1  730.03   526.3  728.88   702.1  727.78   739.1  729.05   794.6  726.69
   805.8  721.76   810.4   721.3   819.2  721.71   837.7   728.5   848.5  727.11
   868.6  727.81   904.1  733.33   964.8  737.84   990.3  738.03   994.5   739.1
  1011.2  747.95  1048.9  753.15  1061.5  758.49  1078.3  762.39  1108.5  773.25
#Mann= 13 ,-1,0
       0      .1       0      70     .07       0  290.91     .05       0
  390.91     .06       0  500.91     .05       0  590.91     .07       0
  600.91     .05       0   805.8    .045       0   819.2      .1       0
   826.7     .08       0   926.7     .07       0  978.65     .06       0
 1088.65      .1       0
Bank Sta=805.8,819.2
XS Rating Curve= 0 ,0
Exp/Cntr(USF)=0,0
Exp/Cntr=0.3,0.1
LCMann Table=0

Chan Stop Cuts=-1
Use User Specified Reach Order=0
Composite Channel Slope=5